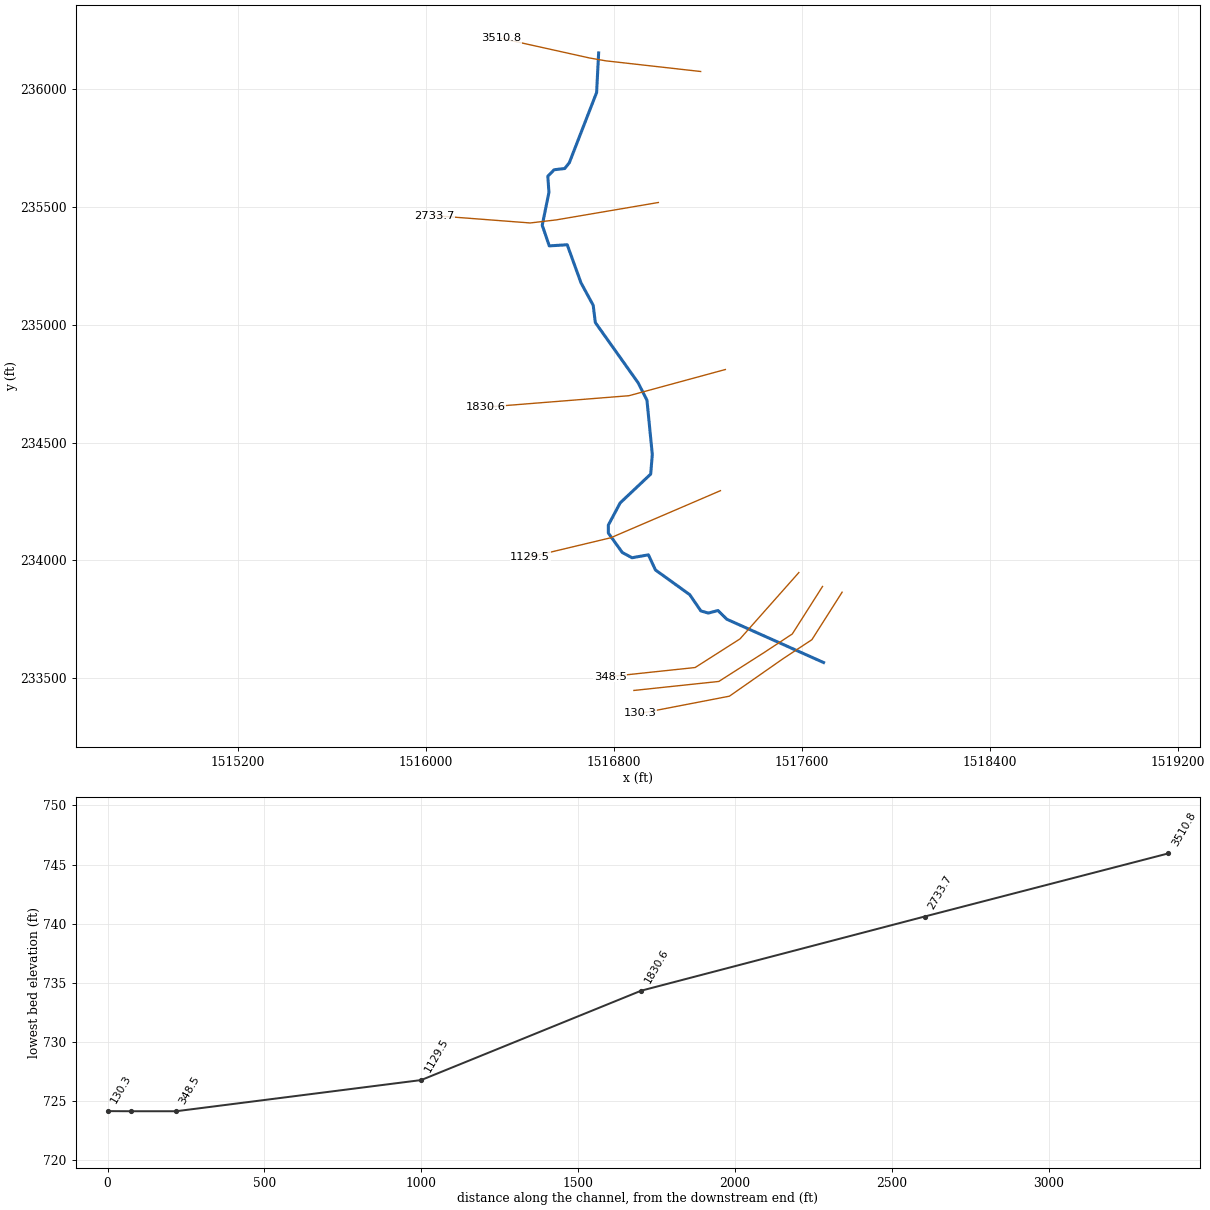
--- INDNRN.prj (project) ---

Proj Title=INDNRN
Current Plan=p01
Default Exp/Contr=0,0
English Units
Geom File=g01
Flow File=f01
Plan File=p01
BEGIN DESCRIPTION:
END DESCRIPTION:
DSS Export Rating Curves= 0
DSS Export Rating Curve Sorted= 0
DSS Export Volume Flow Curves= 0
DXF OffsetX= 0
DXF OffsetY= 0
DXF ScaleX= 0
DXF ScaleY= 0

--- INDNRN.p01 (plan) ---

Plan Title=Floodplain
Program Version=4.00
Geom File=g01
Flow File=f01
K Sum by GR=0
Std Step Tol=0.01
Critical Tol=0.01
Num of Std Step Trials=20
Max Error Tol=0.3
Flow Tol Ratio=0.001
Split Flow NTrial=30
Split Flow Tol=0.02
Split Flow Ratio=0.02
Log Output Level=0
Friction Slope Method=1
Unsteady Friction Slope Method=2
Unsteady Bridges Friction Slope Method=1
Global Log Level=0
CheckData=False
Run HTab=0
Run UNet=0
Run PostProcess=0
UNET Theta=0
UNET Theta Warmup=0
UNET ZTol=0
UNET ZSATol=0
UNET MxIter=0
UNET MaxInSteps=0
UNET DtIC=0
UNET DtMin=0
UNET MaxCRTS=0
UNET WFStab=0
UNET SFStab=0
UNET WFX=0
UNET SFX=0
UNET DSS MLevel=0
UNET DZMax Abort=0
UNET Convert EG Bridges=0
UNET Use Existing IB Tables=0
UNET Froude Limit=0
UNET Froude Power=0
Write IC File=0
Echo Input=False
Echo Output=False
Write Detailed=0

--- INDNRN.f01 (steady flow) ---

Flow Title=NFF Regression Equation
Program Version=4.00
Number of Profiles=1
Profile Names=P100yr
River Rch & RM=INDNRN,Main      ,3510.8
896.0176
River Rch & RM=INDNRN,Main      ,2733.7
1048.450
River Rch & RM=INDNRN,Main      ,348.5
1083.593
Boundary for River Rch & Prof#=INDNRN,Main      ,1
Up Type=0
Dn Type=3
Dn Slope=0.001176

--- INDNRN.g01 (geometry) ---

Geom Title=USGS 10m DEM
Program Version=4.10

River Reach=INDNRN          ,Main
Reach XY= 30
     1516735.553      236152.289     1516726.911      235984.442
     1516610.967      235686.963      1516591.41      235662.271
     1516546.086      235656.908      1516519.41      235629.224
     1516524.271      235561.169     1516495.731      235421.532
      1516525.66      235334.085     1516601.989      235338.977
     1516660.382      235177.835     1516712.466      235082.002
     1516721.493      235009.085     1516903.414      234753.615
     1516940.963      234679.791     1516963.733      234449.728
     1516956.905      234366.294     1516827.084      234244.079
      1516776.66      234149.708     1516776.919      234116.055
     1516836.103      234033.786     1516877.514      234011.496
     1516947.214      234023.871     1516977.049       233959.78
     1517122.882      233854.918     1517170.105      233786.169
     1517202.058      233776.804     1517242.918      233787.745
     1517280.521      233750.752     1517691.956      233567.176

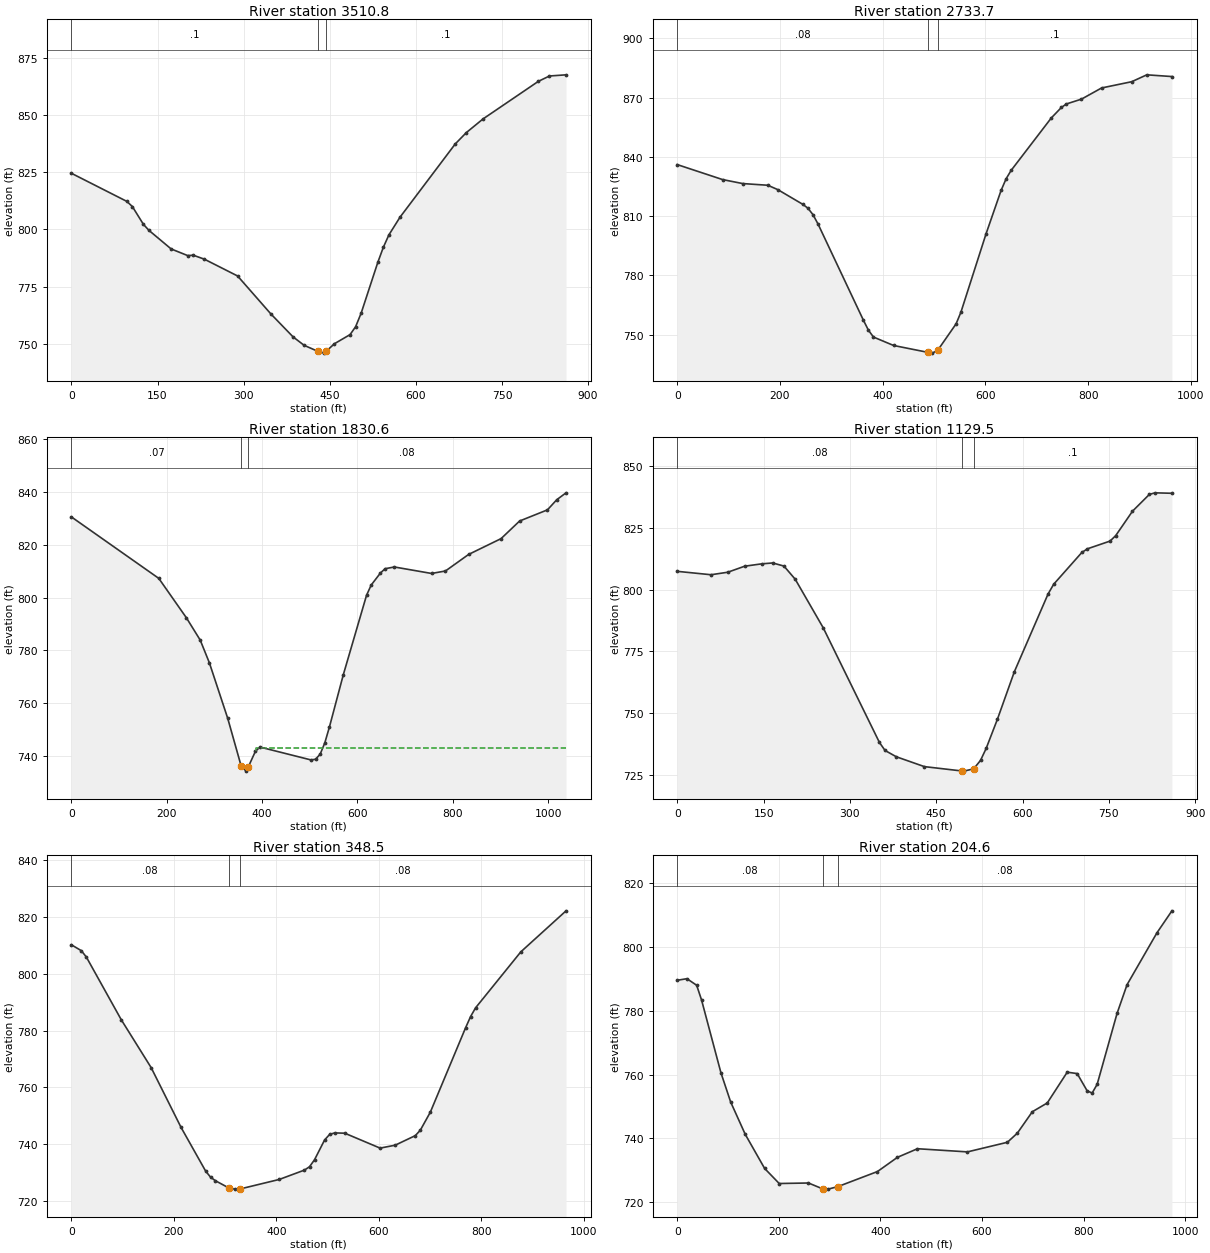
Type RM Length L Ch R = 1 ,3510.8  ,767.7,777.1,783.9
XS GIS Cut Line= 4
     1517169.303      236073.715     1516766.525      236118.854
     1516697.081      236131.007     1516320.344       236214.34
#Sta/Elev= 30
       0  824.48    96.5  812.21   106.2  809.95   125.4  802.19   135.1  799.54
   173.7  791.44   202.6  788.53   212.3   788.7   231.6  786.97   289.5  779.63
   347.4  763.07     386  753.06   405.3  749.36   428.9  746.77   440.6  745.94
   443.9  746.78   458.2  750.05   485.4  754.03   495.1  757.49   504.7  763.39
   533.7  785.56   543.3  792.12     553  797.56   572.3  805.27   668.7  837.32
     688  842.26     717  848.21   813.4  864.63   832.7  866.96   861.6  867.47
#Mann= 3 , 0 , 0
       0      .1       0   428.9    .045       0   443.9      .1       0
Bank Sta=428.9,443.9
XS Rating Curve= 0 ,0
Exp/Cntr=0.3,0.1

Type RM Length L Ch R = 1 ,2733.7  ,897.5,903.2,905.3
XS GIS Cut Line= 4
     1516989.615       235518.16     1516555.104      235444.332
     1516444.476      235431.354     1516034.754      235462.604
#Sta/Elev= 30
       0  836.06    88.2  828.48   127.3  826.46   176.3   825.6   195.9  823.36
   244.8  815.88   254.6  813.92   264.4  810.64   274.2  805.89   362.4  757.25
   372.2  752.18     382  748.73   421.2  744.46   487.2  741.02   496.4  740.59
     507  742.01   542.8  755.41   552.1  761.22     601  800.89   630.4  822.96
   640.2  828.88     650  833.13   728.2  859.69   747.8  864.99   757.6  866.77
   786.9  869.21   826.1  874.87   884.8  878.04   914.1  881.52     963  880.65
#Mann= 3 , 0 , 0
       0     .08       0   487.2    .045       0     507      .1       0
Bank Sta=487.2,507
XS Rating Curve= 0 ,0
Exp/Cntr=0.3,0.1

Type RM Length L Ch R = 1 ,1830.6  ,697,701.1,698.7
XS GIS Cut Line= 3
     1517274.337      234809.826     1516864.615      234698.715
     1516253.504      234650.104
#Sta/Elev= 30
       0  830.57   183.3   807.3   241.2  792.38   270.2  783.93   289.4  775.34
     328  754.25   356.3  736.11   366.6  734.31   371.3     736   385.9  741.77
   395.6  743.42   502.4  738.56   512.1   738.8   521.8  740.72   531.6  745.03
   541.3  751.05   570.5  770.89   619.1  800.89   628.9  804.78   648.3  809.34
   658.1  810.96   677.5  811.61   755.4  809.16   784.6  810.09   833.2  816.36
   901.3  822.35   940.2  829.02   998.6  833.24  1018.1  837.08  1037.6  839.69
#Mann= 3 , 0 , 0
       0     .07       0   356.3    .045       0   371.3     .08       0
#XS Ineff= 2 , 0
                          386.49          743.22
Permanent Ineff=
       F       F
Bank Sta=356.3,371.3
XS Rating Curve= 0 ,0
Exp/Cntr=0.3,0.1

Type RM Length L Ch R = 1 ,1129.5  ,770.5,781.1,779.9
XS GIS Cut Line= 3
     1517253.504      234295.938     1516786.986      234096.172
     1516444.476      234014.688
#Sta/Elev= 30
       0  807.33    58.6  805.96    87.8  806.97   117.1   809.4   146.4  810.34
   165.9  810.71   185.4  809.45     205  804.14   253.7  784.53   351.3  738.32
   361.1  735.07   380.6  732.54   429.4  728.56  493.99726.8203   497.7  726.74
     515  727.64     527  731.07   536.8   735.9   556.4   747.7   585.7  766.78
   644.4   798.2   654.2  802.15   703.1  814.95   712.9  816.43     752  819.53
   761.8   821.7   791.1  831.59   820.4  838.36   830.2     839   859.6  838.82
#Mann= 3 , 0 , 0
       0     .08       0  493.99    .045       0     515      .1       0
Bank Sta=493.99,515
XS Rating Curve= 0 ,0
Exp/Cntr=0.3,0.1

Type RM Length L Ch R = 1 ,348.5   ,149.5,143.8,136.2
XS GIS Cut Line= 5
     1517586.837      233948.715     1517431.665      233774.146
     1517336.837      233667.465     1517145.865      233545.938
     1516784.754      233507.743
#Sta/Elev= 30
       0  810.22    19.5  808.13    29.2   805.9    97.3  783.82   155.7  766.93
   214.1  745.86   262.1  730.46   271.6  728.34   281.1  727.07   307.4  724.52
   319.2   724.1   328.7  724.13   405.8  727.51     455  730.81   464.9  731.99
   474.7  734.45   494.4  741.44   504.2  743.38   514.1  743.92   533.8  743.81
   602.7  738.56   632.1  739.58   671.4  742.95   681.2  744.85   700.8  751.22
   769.5  780.91   779.3  784.88   789.1  787.99   877.5  807.73   965.8  822.19
#Mann= 3 , 0 , 0
       0     .08       0   307.4    .045       0   328.7     .08       0
Bank Sta=307.4,328.7
XS Rating Curve= 0 ,0
Exp/Cntr=0.3,0.1

Type RM Length L Ch R = 1 ,204.6   ,76,74.4,75.2
XS GIS Cut Line= 5
     1517687.532      233889.688      1517559.06      233688.299
     1517437.532      233608.438      1517246.56       233486.91
     1516885.449      233448.715
#Sta/Elev= 30
       0  789.55    19.1  790.04    38.2  787.98    47.8  783.38      86  760.55
   105.1  751.41   133.8  741.28     172  730.58   200.7  725.86   258.3  726.02
   287.4  724.11     297   724.1   316.4   724.9   394.1  729.61   433.5  734.07
   472.9  736.76   571.3  735.77   649.9  738.78   669.5  741.64     699  748.35
   728.4   751.1   767.7  760.75   787.3  760.31   806.9  754.91   816.8  754.22
   826.6  756.93   865.8  779.16   885.5  788.17   944.3  804.41   973.8  811.31
#Mann= 3 , 0 , 0
       0     .08       0   287.4    .045       0   316.4     .08       0
Bank Sta=287.4,316.4
XS Rating Curve= 0 ,0
Exp/Cntr=0.3,0.1

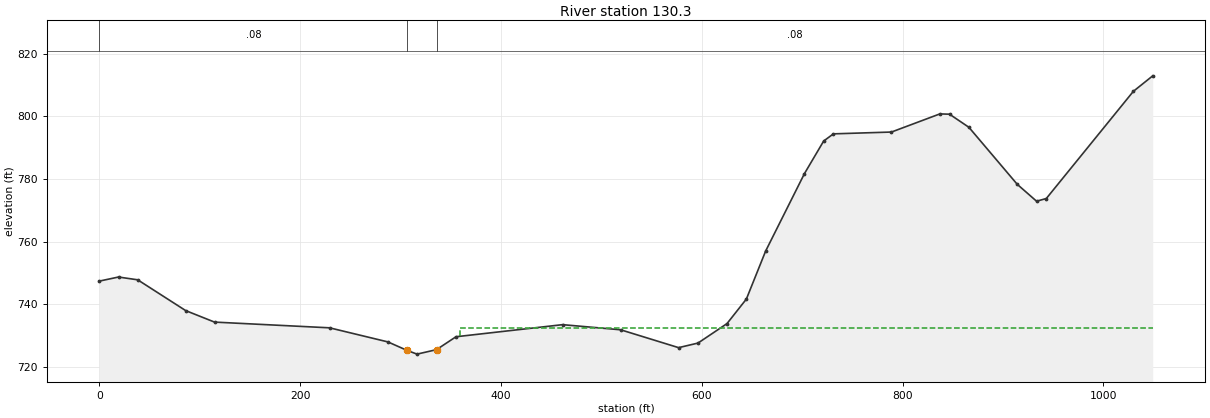
Type RM Length L Ch R = 1 ,130.3   ,122.2,130.3,137.6
XS GIS Cut Line= 5
     1517770.865      233865.382     1517642.393      233663.993
     1517520.865      233584.132     1517291.699       233424.41
     1516913.226      233351.493
#Sta/Elev= 30
       0  747.43    19.1  748.73    38.2  747.84      86  738.01   114.7  734.34
   229.3  732.51   287.4  728.01   306.7  725.27   316.4  724.11   335.8  725.54
   355.2  729.66   461.4  733.52   519.2  731.88   576.9  726.18   596.2  727.64
   625.1  733.86   644.4   741.7   663.6  757.04   702.2  781.74   721.4  792.17
   731.1  794.45   788.9  795.03   837.1  800.82   846.7  800.73     866  796.55
   914.2  778.32   933.4  772.94   943.1   773.8  1029.8  808.03  1049.1  812.98
#Mann= 3 , 0 , 0
       0     .08       0   306.7    .045       0   335.8     .08       0
#XS Ineff= 2 , 0
                           359.2          732.61
Permanent Ineff=
       F       F
Bank Sta=306.7,335.8
XS Rating Curve= 0 ,0
Exp/Cntr=0.3,0.1

Chan Stop Cuts=-1
Use User Specified Reach Order=0
Composite Channel Slope=5